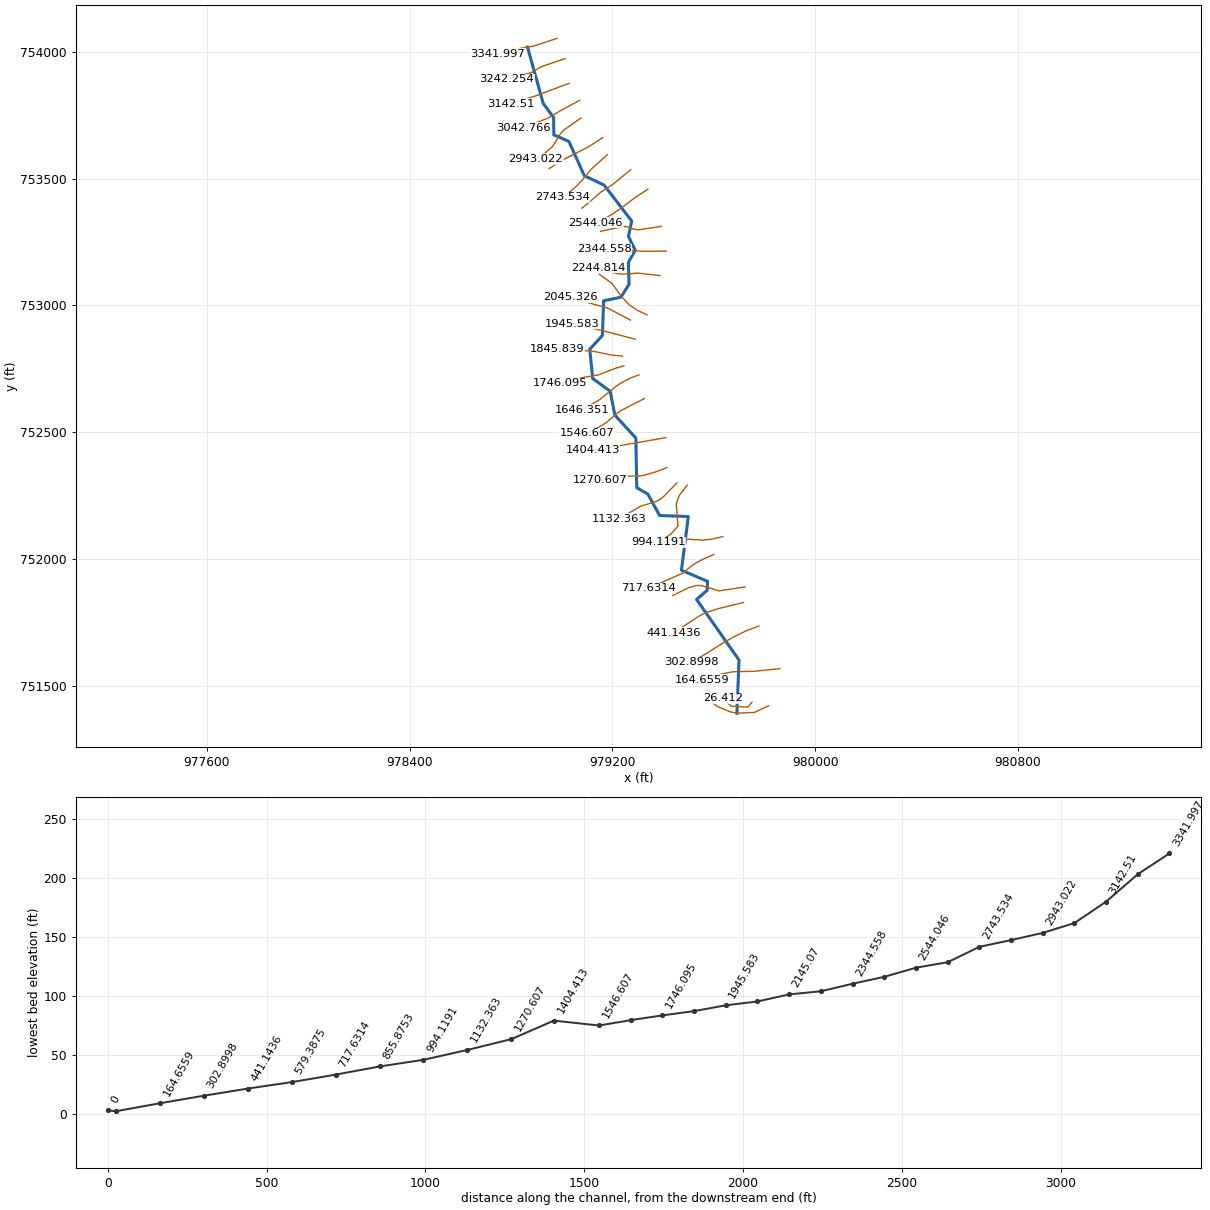
--- 31_ras.prj (project) ---

Proj Title=31
Current Plan=p01
Default Exp/Contr=0.3,0.1
English Units
Geom File=g01
Flow File=f01
Plan File=p01
Y Axis Title=Elevation
X Axis Title(PF)=Main Channel Distance
X Axis Title(XS)=Station
BEGIN DESCRIPTION:
RFD model 31 exported to HEC-RAS
END DESCRIPTION:

--- 31_ras.p01 (plan) ---

Plan Title=Plan 01
Program Version=4.10
Short Identifier=Plan 01
Geom File=g01
Flow File=f01
Subcritical Flow
Calc Critical at every XS
Secant Critical Depth

--- 31_ras.f01 (steady flow) ---

Flow Title=Flow 01
Program Version=5.01
Number of Profiles= 6
Profile Names=10yr,25yr,50yr,100yr,100plus,500yr
River Rch & RM=31,31,3341.997
   76.58  145.95  220.72  303.36   442.9 1032.31
River Rch & RM=31,31,2244.814
   77.17  147.11   222.5  305.84  446.52 1039.79
River Rch & RM=31,31, 2145.07
   78.75  150.19  227.24  312.43  456.15 1059.62
River Rch & RM=31,31,2045.326
   79.34  151.34  229.01   314.9  459.75 1067.02
River Rch & RM=31,31,1945.583
   81.13  154.82  234.34  322.31  470.57 1089.11
River Rch & RM=31,31,1845.839
   82.31  157.11  237.86  327.21  477.72 1103.73
River Rch & RM=31,31,1646.351
   83.48   159.4  241.37  332.09  484.85 1118.28
River Rch & RM=31,31,1546.607
   84.84  162.05  245.45  337.77  493.14 1135.16
River Rch & RM=31,31,1270.607
   86.19  164.69  249.51  343.43   501.4 1151.94
River Rch & RM=31,31,1132.363
   87.35  166.96  252.99  348.26  508.46 1166.25
River Rch & RM=31,31,994.1191
   88.12  168.46   255.3  351.48  513.16 1175.75
River Rch & RM=31,31,717.6314
   93.47   178.9  271.35  373.83  545.79 1241.43
River Rch & RM=31,31,579.3875
   96.28   184.4  279.82  385.64  563.04 1276.06
River Rch & RM=31,31,441.1436
   97.57  186.93  283.72  391.09  570.99 1292.09
River Rch & RM=31,31,164.6559
  101.43  194.51  295.41  407.42  594.83 1339.74
River Rch & RM=31,31,  26.412
  101.98  195.58  297.06  409.72   598.2 1346.49
Boundary for River Rch & Prof#=31,31,1
Up Type= 0
Dn Type= 2
Boundary for River Rch & Prof#=31,31,2
Up Type= 0
Dn Type= 2
Boundary for River Rch & Prof#=31,31,2
Up Type= 0
Dn Type= 2
Boundary for River Rch & Prof#=31,31,2
Up Type= 0
Dn Type= 2
Boundary for River Rch & Prof#=31,31,2
Up Type= 0
Dn Type= 2
Boundary for River Rch & Prof#=31,31,2
Up Type= 0
Dn Type= 2

--- 31_ras.g01 (geometry) ---

Geom Title=31
Program Version=4.10

River Reach=31,31
Reach XY= 30
978865.028923781 754019.56481142978926.974985392753796.685850749
978968.267583821753740.915100808 978968.70161164 753672.77273968
979028.163417193753647.165100808979089.361333835753511.314406355
 979167.48633385753474.422045236 979275.99327828753332.928989702
979263.406472713753272.165100788979289.882167163753217.477600788
979262.972444955753169.734545217979265.776074219753083.593650573
979233.458556058 753032.23454524979165.403000521753018.345656345
979160.541889402752881.540100805979110.541889386 752826.67898968
979122.347444938752711.401211909979191.097444955752661.401211913
979209.847444953752566.956767476979292.486333834752476.678989686
 979295.95855606752280.845656365 979339.70855606752255.845656357
979386.236333862752171.123434123 979499.43077831752166.956767458
979472.347444985751955.151211905979575.125222702751911.401211891
979573.736333863751875.984545227979532.069667178751839.873434116
979699.430778282751600.984545227979691.097444954751390.567878556

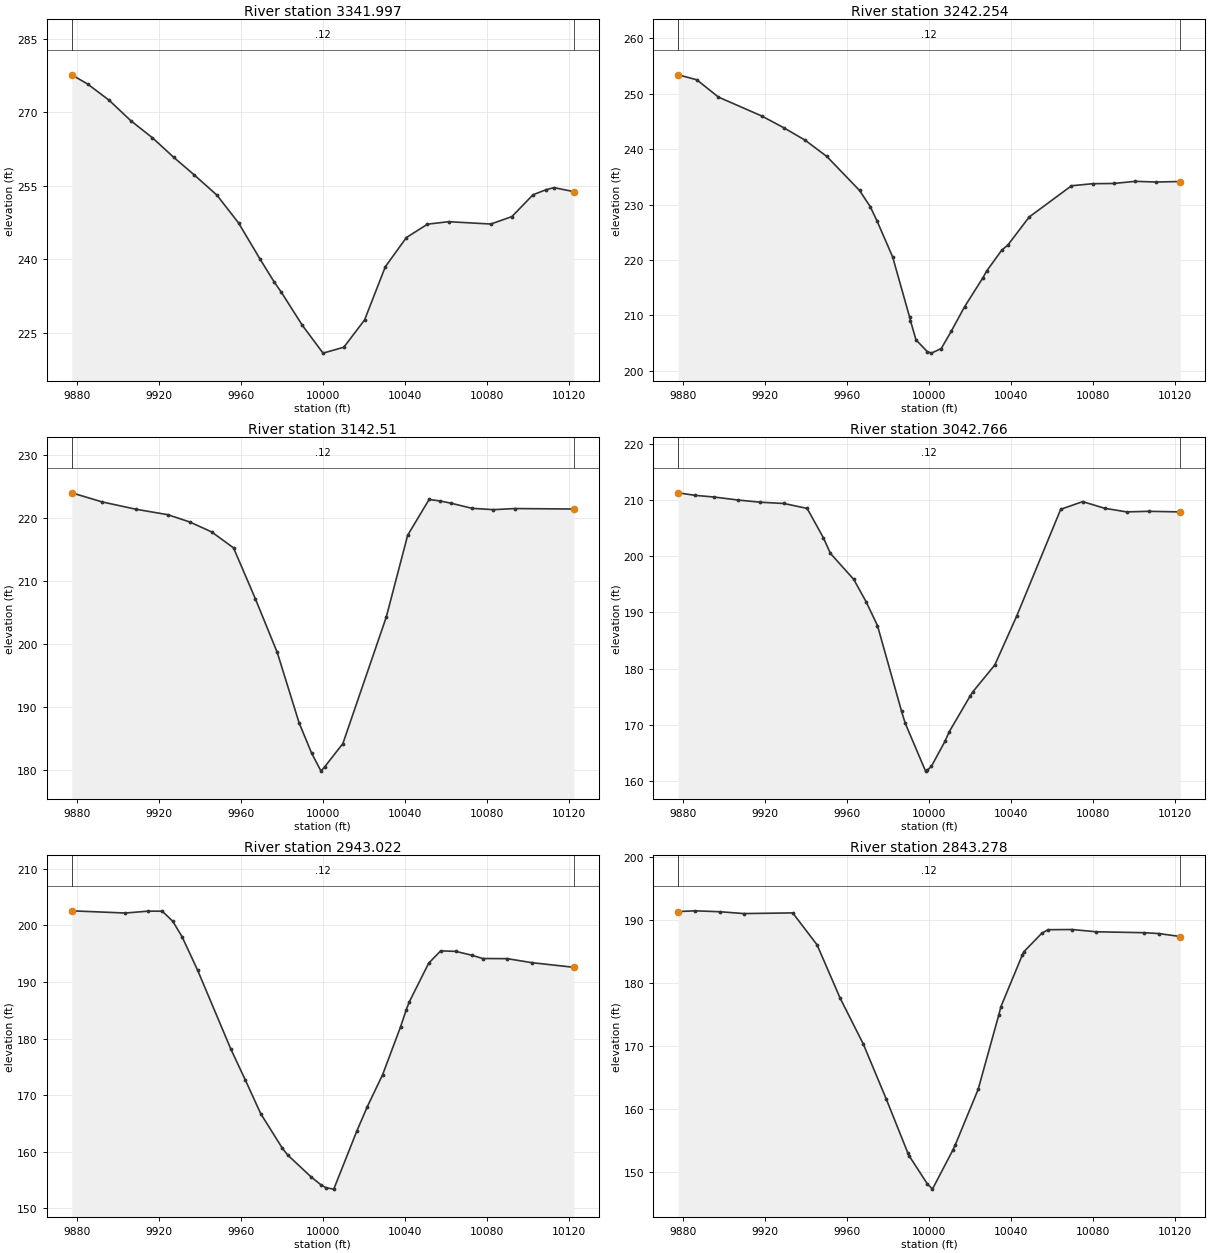
Type RM Length L Ch R = 1 ,3341.997,99.743900,99.743900,99.743900
XS GIS Cut Line= 6
978982.389549824754053.536282714 978888.57730617754022.918970359
978866.124945613754018.671091026978864.135203387754018.468789588
978834.115423028754013.490634263978745.627294453753991.736032493
#Sta/Elev= 26
9877.467277.5972 9885.24 275.7159895.759272.39489906.279268.24629916.798 264.774
9927.317260.75219937.211257.20429948.355253.05479958.874247.39749969.393240.0128
9976.149235.4387 9979.79233.26039989.968226.550110000.13220.849410010.26222.0514
 10020.4227.616310030.53238.471110040.82244.424210051.11247.143110061.41247.6525
10082.01247.173310092.31248.6899 10102.6253.136710108.88254.1549 10112.9254.5943
10122.55253.7758
#Mann= 3 , 0 , 0
9877.467    0.12       09877.467    0.12       010122.55    0.12       0
#XS Ineff= 2 , 0
       0                               0
Bank Sta=9877.467,10122.55
Exp/Cntr=0.3,0.1

Type RM Length L Ch R = 1 ,3242.254,99.744000,99.744000,99.744000
XS GIS Cut Line= 6
 979013.56610619753973.879430478978921.897595839753942.229100102
978907.556400944753935.242235055978890.945581511 753923.59859022
978876.856087045753917.378589483978783.657705079753892.625553514
#Sta/Elev= 30
9877.457253.4232 9886.52252.52689897.099249.40469918.257 245.9899928.837243.9034
9939.416241.62119949.995238.68989965.946232.56389971.154 229.6529974.436227.1008
9982.109220.56499990.389209.70959990.815209.06799993.496205.6073    9999203.4854
   10001203.204210005.81204.020910010.69 207.13510017.19211.553910026.09216.7607
10028.01218.025310035.36221.786210038.36 222.71110048.71227.7544 10069.4 233.405
10079.75233.778210090.09233.818510100.44234.203810110.79234.082410122.52234.1738
#Mann= 3 , 0 , 0
9877.457    0.12       09877.457    0.12       010122.52    0.12       0
#XS Ineff= 2 , 0
       0                               0
Bank Sta=9877.457,10122.52
Exp/Cntr=0.3,0.1

Type RM Length L Ch R = 1 , 3142.51,99.743900,99.743900,99.743900
XS GIS Cut Line= 5
979028.993417572753875.938481128978915.116681947753833.425047939
978913.258089793753832.686376698 978893.76661121753825.440792986
978797.489456979753795.678188523
#Sta/Elev= 23
9877.446223.99799892.383222.54819908.721221.40179924.406220.5275 9935.08219.3736
9945.754217.80299956.428 215.2729967.102207.19079977.776198.6956 9988.45187.5356
9994.497182.78559999.126179.8962   10001180.612610009.81 184.26710030.97204.2888
10041.44217.2792 10051.9222.947110057.15 222.71310062.37222.371310072.84221.5438
10083.31221.330310093.77221.505210122.57221.4324
#Mann= 3 , 0 , 0
9877.446    0.12       09877.446    0.12       010122.57    0.12       0
#XS Ineff= 2 , 0
       0                               0
Bank Sta=9877.446,10122.57
Exp/Cntr=0.3,0.1

Type RM Length L Ch R = 1 ,3042.766,99.743900,99.743900,99.743900
XS GIS Cut Line= 6
979070.247941881753808.903882606978989.746906477753765.003817049
978964.296282504753749.362654726978962.587885391753748.322760835
978946.261352769753738.820200096978850.574378473753701.667663871
#Sta/Elev= 29
9877.434211.32029885.588210.87249894.802210.57679906.475210.04329917.583209.6418
9928.973209.42349940.363208.54349948.248203.34439951.754200.52029963.144195.8848
9969.135191.91529974.699187.66369986.436172.42289988.233170.27319998.174161.7261
    9999161.9033   10001 162.56210007.61167.016610009.78168.778210019.89175.0832
10021.24175.858110031.97 180.638 10042.7189.385610064.15208.386710074.88209.7528
10085.61208.565410096.33207.922810107.06208.026210122.54207.9176
#Mann= 3 , 0 , 0
9877.434    0.12       09877.434    0.12       010122.54    0.12       0
#XS Ineff= 2 , 0
       0                               0
Bank Sta=9877.434,10122.54
Exp/Cntr=0.3,0.1

Type RM Length L Ch R = 1 ,2943.022,99.743900,99.743900,99.743900
XS GIS Cut Line= 6
979075.986099489753739.554394406979006.902713194 753690.62580054
978993.967727096753675.894051553978963.240763896753625.886919607
978934.632732293753601.302009397978897.800351404753577.276868006
#Sta/Elev= 30
9877.519202.58199903.706202.19469914.792202.52929921.698202.51419926.821200.7206
9931.309198.01569938.877192.12289955.121178.15269962.227172.65619969.714166.7298
9980.267160.62579982.836159.44189994.073 155.631    9999154.186910001.52153.6473
10005.33153.401910016.65163.721910021.68167.959610029.19173.642410037.91182.0736
10040.76185.139410042.12186.451310051.63193.322810057.47195.504310064.81195.4216
10072.81194.7252   10078194.153510089.99194.130310101.92193.422710122.46192.6037
#Mann= 3 , 0 , 0
9877.519    0.12       09877.519    0.12       010122.46    0.12       0
#XS Ineff= 2 , 0
       0                               0
Bank Sta=9877.519,10122.46
Exp/Cntr=0.3,0.1

Type RM Length L Ch R = 1 ,2843.278,99.744000,99.744000,99.744000
XS GIS Cut Line= 6
979162.010444594753661.888650658979103.577532784753624.351062538
979057.164224162753600.709926698979055.487945096753599.619014928
979015.606695697753579.890987684 978949.97294064753539.515766029
#Sta/Elev= 27
9877.461191.29669885.794191.40979897.679191.26989909.565190.97429933.336 191.082
9945.222186.02689956.539177.53879967.761170.32679978.984161.60149989.548153.0377
9990.206152.5682    9999148.166110001.54147.301410011.42153.4334 10012.7154.3225
10023.86163.106310033.97174.947210035.01176.243210045.49184.467710046.21184.9378
10054.83187.822910057.95188.417810069.69188.447710081.43188.091410104.91187.9423
10112.09187.805810122.55187.3361
#Mann= 3 , 0 , 0
9877.461    0.12       09877.461    0.12       010122.55    0.12       0
#XS Ineff= 2 , 0
       0                               0
Bank Sta=9877.461,10122.55
Exp/Cntr=0.3,0.1

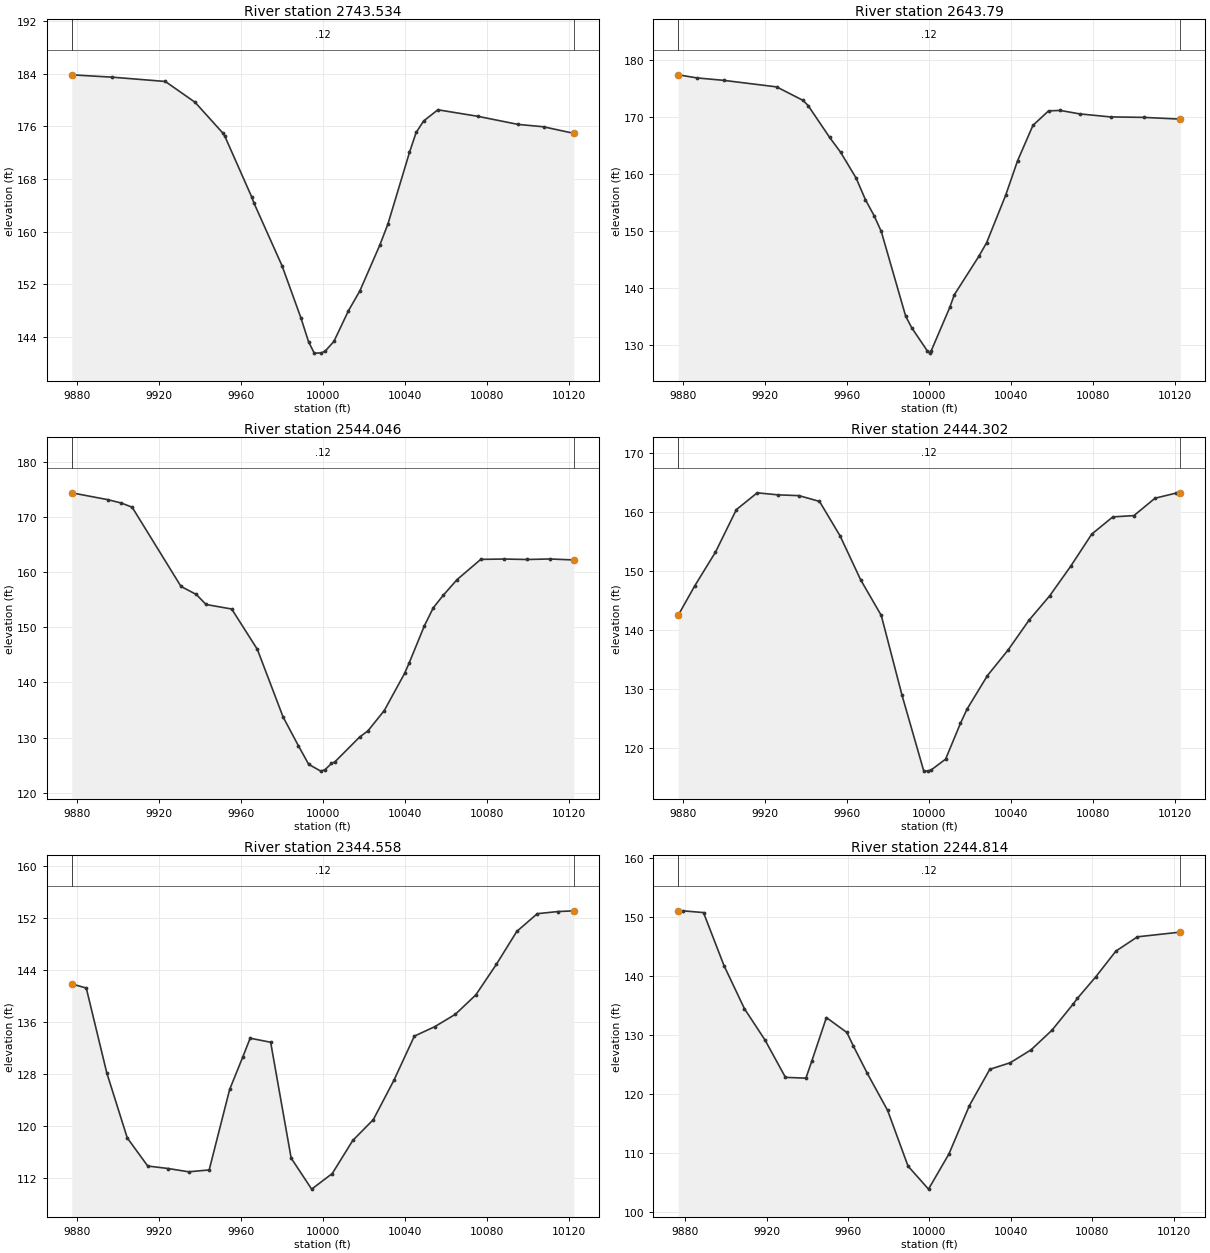
Type RM Length L Ch R = 1 ,2743.534,99.743900,99.743900,99.743900
XS GIS Cut Line= 6
979180.129200779753594.632667441979117.076468232 753538.09323809
979080.672127097 753493.79565822 979060.22405677753472.347216099
979032.182130952753447.888972261979003.049855583753426.572319389
#Sta/Elev= 27
9877.452183.8055 9897.33183.4467 9923.12182.79689937.634179.64019951.241174.9522
9952.149174.49799965.265165.27659966.348164.37319980.153154.77759989.306146.9153
 9993.02143.30529995.808141.5673    9999141.5923   10001141.8212 10005.4143.3445
10012.52148.009710018.06151.0076 10027.8157.958410031.73161.124310042.29172.0278
10045.55175.061710049.22176.809210056.15178.498910075.61177.512210095.33176.2782
10107.72175.919810122.52174.9219
#Mann= 3 , 0 , 0
9877.452    0.12       09877.452    0.12       010122.52    0.12       0
#XS Ineff= 2 , 0
       0                               0
Bank Sta=9877.452,10122.52
Exp/Cntr=0.3,0.1

Type RM Length L Ch R = 1 , 2643.79,99.743900,99.743900,99.743900
XS GIS Cut Line= 6
979272.153625671753535.190022728979201.483482729753477.296472801
979174.414683835753459.898513825979153.340327884753446.203222085
979107.060973551753405.400832304979079.841636741753383.891597692
#Sta/Elev= 30
9877.462177.3991 9886.71176.85199899.637176.42939925.491175.27989938.418172.9009
9940.882171.98699951.345166.41399956.662163.82189964.272159.27119968.818155.4703
9973.038152.67129976.546149.89969988.465135.00699991.414132.9682    9999128.9155
10000.33128.5042   10001128.964710009.99136.536810012.23138.767610024.15145.4951
10027.95147.880710037.25156.218110043.07162.286410050.58168.5151 10058.2 171.065
10063.92171.145510073.32170.540310088.48170.003410104.61169.923710122.52169.6176
#Mann= 3 , 0 , 0
9877.462    0.12       09877.462    0.12       010122.52    0.12       0
#XS Ineff= 2 , 0
       0                               0
Bank Sta=9877.462,10122.52
Exp/Cntr=0.3,0.1

Type RM Length L Ch R = 1 ,2544.046,99.743900,99.743900,99.743900
XS GIS Cut Line= 6
979339.726768856753458.191013005979289.962349441753425.891537767
979235.659102762753384.443857882979198.733018845753359.577558323
979166.687330905753340.876986557979134.387545257753325.397900416
#Sta/Elev= 30
9877.457174.47479895.013173.23649901.686172.61759906.935171.85779930.778157.4618
9938.264155.9988    9943154.18019955.527 153.3559968.054146.02329980.581133.7665
9988.074128.51459993.109125.1265    9999123.8898   10001124.128910004.23125.2773
10005.91125.579210017.96130.082510022.02131.205710030.02134.907710039.92141.6513
10042.07143.471310049.63150.340110053.95153.590410058.71155.816510065.53158.6974
10077.11  162.38 10088.6162.440510099.69162.356610110.78162.451710122.55162.2734
#Mann= 3 , 0 , 0
9877.457    0.12       09877.457    0.12       010122.55    0.12       0
#XS Ineff= 2 , 0
       0                               0
Bank Sta=9877.457,10122.55
Exp/Cntr=0.3,0.1

Type RM Length L Ch R = 1 ,2444.302,99.743900,99.743900,99.743900
XS GIS Cut Line= 6
979392.841915745753311.737927877979304.921116499753298.234848484
979285.496039431753300.558109184979258.188880558753310.392811219
979242.027772228753311.304409628979153.010204697753292.232768844
#Sta/Elev= 29
9877.528142.51679885.512 147.4519895.694153.19779905.876 160.3929916.057163.2357
9926.239162.89019936.401162.76249946.438161.78499956.474155.9543 9966.51148.5214
9976.581142.47839986.679129.00139997.286116.17589999.411116.1317   10001116.3515
10007.95118.157610015.18 124.20210018.37126.601210028.39132.314410038.49136.6508
10048.63141.666210058.77145.820610068.95 150.79510079.24156.241210089.54159.1657
10099.83  159.3810110.12162.325210120.42163.192810122.46163.2214
#Mann= 3 , 0 , 0
9877.528    0.12       09877.528    0.12       010122.46    0.12       0
#XS Ineff= 2 , 0
       09936.384                       0
Bank Sta=9877.528,10122.46
Exp/Cntr=0.3,0.1

Type RM Length L Ch R = 1 ,2344.558,99.744000,99.744000,99.744000
XS GIS Cut Line= 6
979412.081112964 753214.20051476 979328.62488169 753213.42917279
 979290.57511997753215.257202593979288.595220982753215.540045301
979255.255238818753218.055642145979167.166879209753220.856181253
#Sta/Elev= 27
9877.447141.82039884.528141.19819894.528128.17189904.529118.16879914.529  113.84
 9924.53 113.454 9934.53112.94999944.531113.23639954.531125.61029960.906130.5724
9964.535133.48639974.547132.85929984.558115.0527 9994.57110.286110004.61112.6781
10014.63117.762610024.66120.967910034.69126.9978 10044.7 133.803 10054.7135.2623
10064.71137.156110074.71 140.14110084.72144.826810094.72 149.90210104.73152.6248
10114.73  152.9510122.57153.0627
#Mann= 3 , 0 , 0
9877.447    0.12       09877.447    0.12       010122.57    0.12       0
#XS Ineff= 2 , 0
       09968.092                       0
Bank Sta=9877.447,10122.57
Exp/Cntr=0.3,0.1

Type RM Length L Ch R = 1 ,2244.814,99.743900,99.743900,99.743900
XS GIS Cut Line= 6
979387.337695769753117.564925162979301.775382292753127.316251657
 979244.80510514753123.602823371979223.239163639753124.704899324
979192.866636087753131.973053177979145.139719217753148.814116386
#Sta/Elev= 28
9876.624151.02679878.977151.05159889.042150.75529899.107 141.7769909.171134.4525
9919.236129.16719929.301122.82519939.366 122.6919942.285125.6185 9949.43 132.962
9959.495130.42869962.741128.09939969.516123.50919979.516117.22349989.543107.7819
9999.603103.879910009.66 109.861 10019.7118.045210029.71124.191810039.73 125.299
10049.96127.483710060.25130.809210070.53135.190310072.72136.198510081.82 139.883
10091.67144.224810102.27146.647510123.33147.4445
#Mann= 3 , 0 , 0
9876.624    0.12       09876.624    0.12       010123.33    0.12       0
#XS Ineff= 2 , 0
       09965.251                       0
Bank Sta=9876.624,10123.33
Exp/Cntr=0.3,0.1

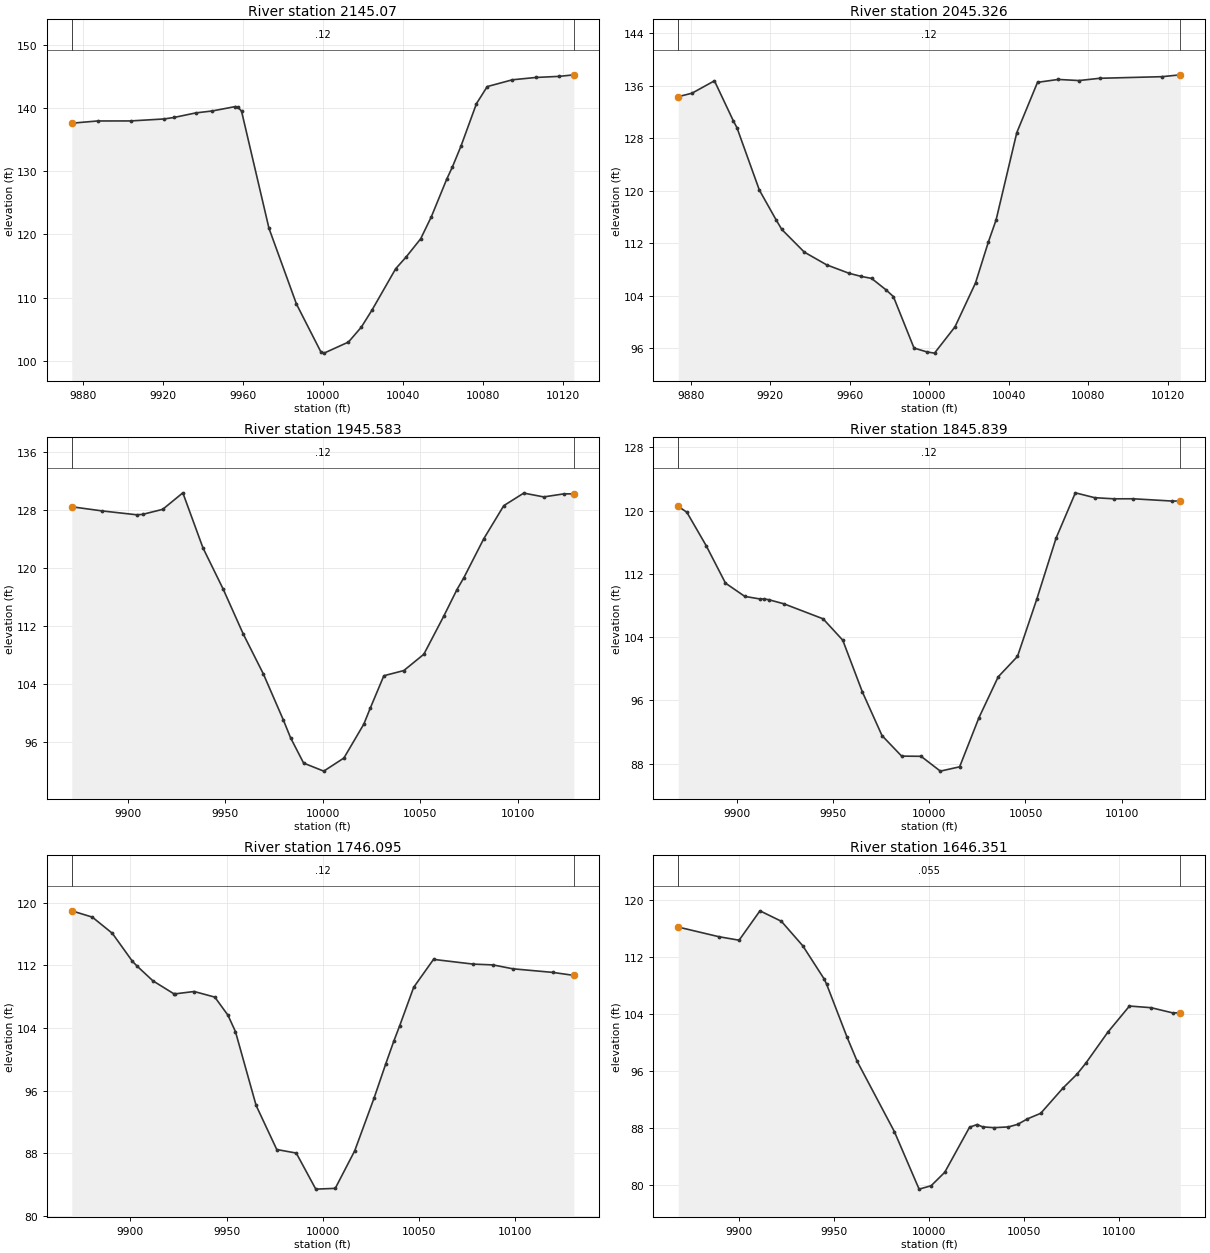
Type RM Length L Ch R = 1 , 2145.07,99.743900,99.743900,99.743900
XS GIS Cut Line= 6
979336.766962446752962.827848227979299.113394159 752979.94157294
 979265.75541054753002.810360941979233.220336844753037.375048778
979198.252010193753087.229643865979148.884846329753122.235741097
#Sta/Elev= 30
9874.477137.60339887.402137.95569903.894137.96049920.659138.2741 9925.53138.5063
9936.527139.23259944.679139.53659956.338140.23549957.439 140.1549959.347139.5239
9973.091120.96959986.834108.9892    9999101.444210000.62101.229410012.82102.9806
10019.25105.337110024.63108.060910036.45114.588910041.51116.380810048.93119.3154
10054.26122.800710061.93128.727210064.83130.7103 10069.1133.989710076.83140.7018
10082.22143.397610094.83 144.47210106.58144.838810118.33145.014210125.52145.2549
#Mann= 3 , 0 , 0
9874.477    0.12       09874.477    0.12       010125.52    0.12       0
#XS Ineff= 2 , 0
       0                               0
Bank Sta=9874.477,10125.52
Exp/Cntr=0.3,0.1

Type RM Length L Ch R = 1 ,2045.326,99.743900,99.743900,99.743900
XS GIS Cut Line= 6
979271.131933655752942.053127927979178.617832984752990.770069145
979158.619066347752996.398884364979156.638081801752996.674021107
979128.725987404753003.713752139979036.101553668753031.308395746
#Sta/Elev= 29
9873.667134.34139880.597134.87089891.899136.75829901.454130.62479903.201129.6286
9914.502120.10569922.916115.57319925.804114.10139937.106110.65289948.408   108.7
9959.709107.4136 9965.84106.93649971.011106.63939978.224104.90219981.983103.8683
9992.37196.01748    999995.4200910002.6995.24613   1001399.2572910023.32105.9393
10029.79112.183710033.67115.529810044.11128.864210054.54136.525110064.98136.9678
10075.41136.797610085.85137.143410117.15137.387810126.43137.6706
#Mann= 3 , 0 , 0
9873.667    0.12       09873.667    0.12       010126.43    0.12       0
#XS Ineff= 2 , 0
       0                               0
Bank Sta=9873.667,10126.43
Exp/Cntr=0.3,0.1

Type RM Length L Ch R = 1 ,1945.583,99.743900,99.743900,99.743900
XS GIS Cut Line= 5
979290.177252812752866.563909965979166.435670682752898.939231321
979164.509278079752899.476829257979155.983091043752901.732088832
979039.932530871752928.477721555
#Sta/Elev= 29
9871.093128.42619886.781 127.8529904.422127.32189907.455 127.3779917.791128.0732
9928.128130.34989938.464122.75789948.801 117.0969959.138110.88989969.474105.3777
9979.81198.982159983.43796.578279990.14793.0790510000.4991.9716610010.8393.77728
10021.0998.4689610024.37100.659510031.35105.126810041.61105.841710051.88108.0886
10062.14113.3579 10068.9117.0145 10072.4118.630910082.66124.019610092.93128.5807
10103.19130.313210113.45129.786310123.71130.205310128.91130.2048
#Mann= 3 , 0 , 0
9871.093    0.12       09871.093    0.12       010128.91    0.12       0
#XS Ineff= 2 , 0
       0                               0
Bank Sta=9871.093,10128.91
Exp/Cntr=0.3,0.1

Type RM Length L Ch R = 1 ,1845.839,99.744000,99.744000,99.744000
XS GIS Cut Line= 6
979239.455127056752800.048605594979196.989817949752804.113567136
 979120.54467434752819.734762727979111.741493332 752820.10720784
979109.742410974752820.046629584978980.582226328752829.426173219
#Sta/Elev= 28
9869.505120.5409 9873.98119.79719884.026115.56869894.072110.82689904.117109.1479
9912.164108.81669914.195108.82629916.592108.72829924.402108.21329944.815106.3117
9955.022103.61099965.22897.061739975.43591.537569985.64288.941239995.73988.91902
10005.7587.0422210015.7887.5867510025.81 93.797210035.8398.9699810045.86101.5578
10055.89108.797410065.91116.515610075.94122.252410085.97121.638410095.99 121.494
10106.02121.499510126.07121.2138 10130.5121.2127
#Mann= 3 , 0 , 0
9869.505    0.12       09869.505    0.12       0 10130.5    0.12       0
#XS Ineff= 2 , 0
       0                               0
Bank Sta=9869.505,10130.5
Exp/Cntr=0.3,0.1

Type RM Length L Ch R = 1 ,1746.095,99.743900,99.743900,99.743900
XS GIS Cut Line= 6
979245.261155086752761.605462421979212.619873677752752.153959784
979144.939383252752725.774386147979122.420856847752721.946575815
979089.024224994752716.759909094978994.289947304752692.769795356
#Sta/Elev= 29
9869.537118.94079880.219118.1389 9890.63116.07179901.041112.50959903.519111.8813
9911.697110.0165 9922.43108.38419923.218108.34919933.162108.64979943.895 107.935
9950.754105.61489954.628103.53119965.36194.119429976.09388.49253 9986.2488.03994
9996.38483.43984 10006.583.5370610016.6288.3294610026.7595.10207 10032.899.45074
10036.95102.323210039.97104.264310047.27109.183210057.58112.746110078.22112.1435
10088.53112.040410098.85111.545210119.48 111.08910130.53110.7041
#Mann= 3 , 0 , 0
9869.537    0.12       09869.537    0.12       010130.53    0.12       0
#XS Ineff= 2 , 0
       0                               0
Bank Sta=9869.537,10130.53
Exp/Cntr=0.3,0.1

Type RM Length L Ch R = 1 ,1646.351,99.743900,99.743900,99.743900
XS GIS Cut Line= 6
979304.992426373752726.147000235979270.097020926752713.052627886
979233.840620238752694.217179867979210.673617343752678.032366198
979150.872903503752628.969555699979081.513268012752588.314431641
#Sta/Elev= 30
 9867.89116.22369889.243114.86849899.924 114.3749910.905118.50619922.174117.0357
9933.443113.59129944.712108.91789946.018108.16819956.803100.69999962.11297.31898
9981.65987.454759994.66679.37069   1000179.8467910008.1581.7343410021.2388.07988
10025.2388.4534310028.1288.1254510034.0488.0136710041.6788.1181710046.5588.47909
10051.7189.2535610058.6790.0331410070.5293.6200210077.7695.5304410082.3797.06835
10093.98101.431310105.38105.117610116.78104.884110128.18104.151310132.15104.1813
#Mann= 3 , 0 , 0
 9867.89   0.055       0 9867.89   0.055       010132.15   0.055       0
#XS Ineff= 2 , 0
       0                               0
Bank Sta=9867.89,10132.15
Exp/Cntr=0.3,0.1

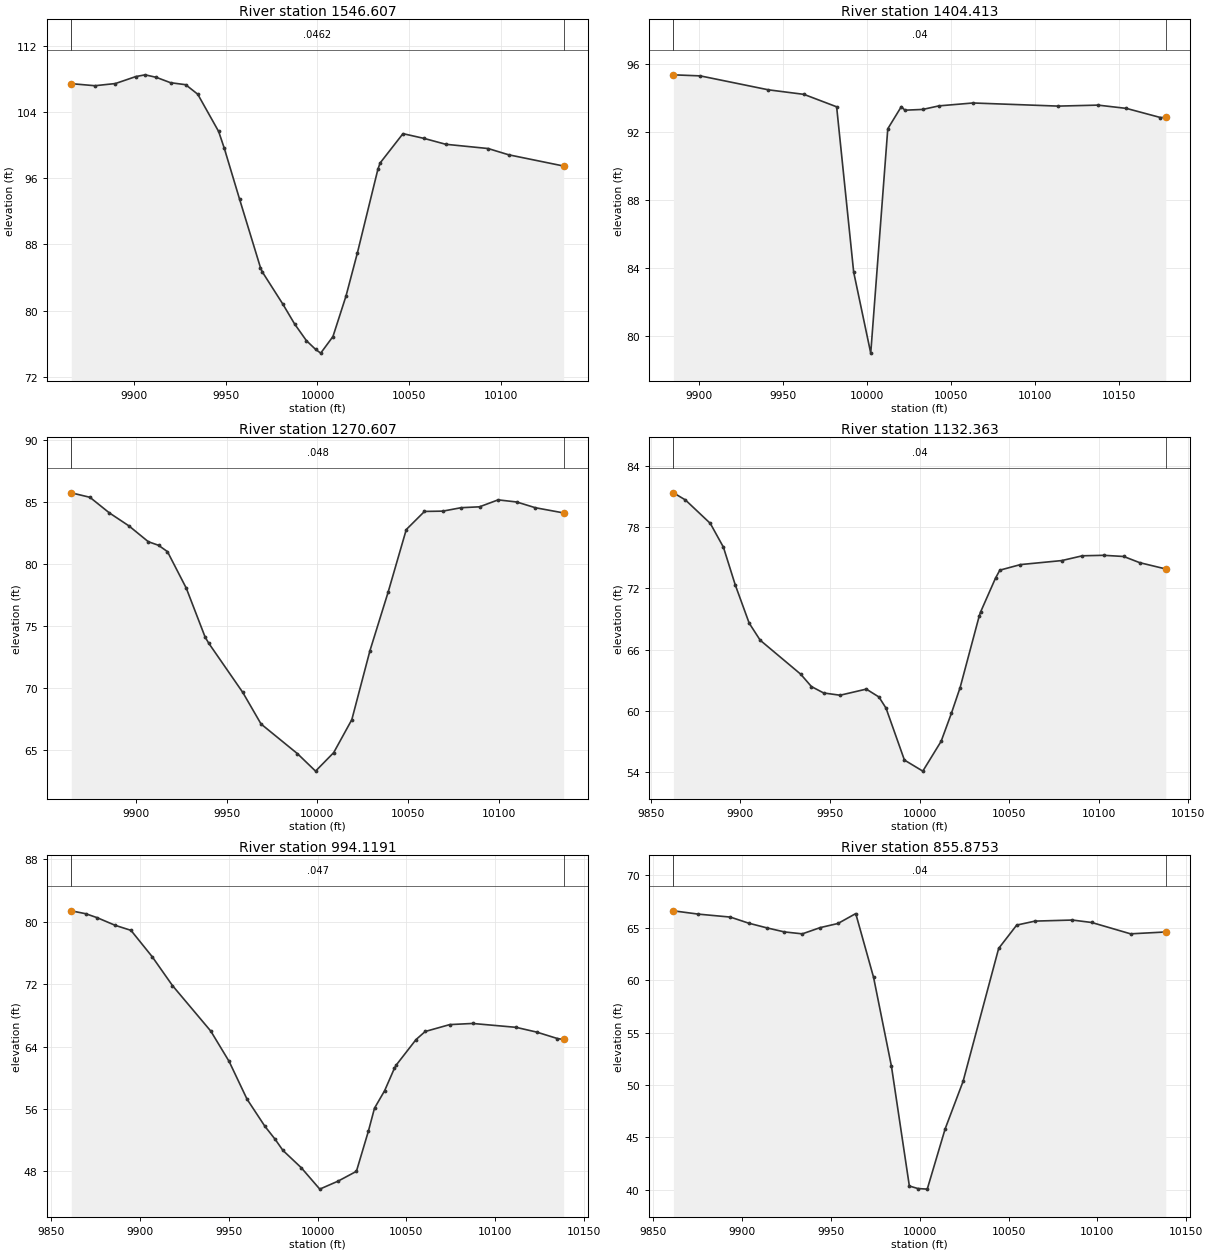
Type RM Length L Ch R = 1 ,1546.607,142.193800,142.193800,142.193800
XS GIS Cut Line= 6
979326.550929974752632.687194596979235.294282698752585.795678791
979219.922992374752575.196222933 979174.94542796752536.856825557
979137.680733477752514.815256559979098.205421908752495.174315922
#Sta/Elev= 30
9865.986107.47419878.848107.22559889.983107.48869901.118108.33479906.197108.5446
9912.253108.23999920.025107.58959928.256107.34879934.829106.1944  9946.2101.6834
9949.26799.65276 9957.5793.500769968.96485.196339970.00884.663749981.11180.78842
9987.56778.367289993.97676.35192    999975.2887910001.7674.8407310008.4276.84978
10015.52 81.752110021.6786.9337610032.9197.12848 10034.197.8716110046.54101.4204
10058.16100.836710069.78100.134810092.8999.6187410104.0698.8606610133.9997.49806
#Mann= 3 , 0 , 0
9865.986  0.0462       09865.986  0.0462       010133.99  0.0462       0
#XS Ineff= 2 , 0
       0                               0
Bank Sta=9865.986,10133.99
Exp/Cntr=0.3,0.1

Type RM Length L Ch R = 1 ,1404.413,133.806200,133.806200,133.806200
XS GIS Cut Line= 3
979410.737270743752478.396552205979264.482062221752452.801890746
979121.883233964752428.121324316
#Sta/Elev= 18
 9884.7395.356539900.70695.294379941.31494.473599962.445 94.20659981.92293.47468
9992.07483.7414510002.2378.9748510012.3892.1809610020.46 93.487810022.53 93.2746
10033.21 93.319610042.8393.5287510063.1393.6992310113.8793.5156110137.5993.57337
10154.4793.3807710174.7692.8430610177.9392.84522
#Mann= 3 , 0 , 0
 9884.73    0.04       0 9884.73    0.04       010177.93    0.04       0
#XS Ineff= 2 , 0
       0                               0
Bank Sta=9884.73,10177.93
Exp/Cntr=0.3,0.1

Type RM Length L Ch R = 1 ,1270.607,138.243900,138.243900,138.243900
XS GIS Cut Line= 6
979414.578459807752360.179226438 979369.72653973752342.604616763
979325.314816162752329.942095437979303.869310479752327.356575688
979226.896958531752325.744719354979149.798024548752310.090365715
#Sta/Elev= 27
9864.14885.753169874.43685.391839885.17684.130759895.91683.087599906.65681.80531
 9912.3281.513779917.23581.001849927.63478.046549938.032 74.09449940.05573.59531
9958.81969.624679968.891 67.07649988.97364.681919998.97363.2707610008.9864.76655
10018.9867.4284610028.9973.0036410039.0277.7272710049.0482.7864110059.0984.24952
10069.2184.2744510079.3384.5521610089.4684.6230710099.7385.18438   1011085.01296
10120.2784.5499110135.8984.12909
#Mann= 3 , 0 , 0
9864.148   0.048       09864.148   0.048       010135.89   0.048       0
#XS Ineff= 2 , 0
       0                               0
Bank Sta=9864.148,10135.89
Exp/Cntr=0.3,0.1

Type RM Length L Ch R = 1 ,1132.363,138.243900,138.243900,138.243900
XS GIS Cut Line= 6
979454.430038624752299.782670284979404.847820762 752248.62586257
979385.556788691 752233.18700364979366.147949175 752223.79142487
979314.320880266752209.143767939979224.612124947752157.757043155
#Sta/Elev= 30
9862.59781.370169869.25780.676699883.18378.374469890.51476.041189897.10972.35158
9904.88368.603919911.03666.92803 9933.6263.605129939.64162.387739946.452 61.7603
9955.64561.538569970.27662.137949977.33661.365019981.28960.272649991.55855.18653
10001.8254.1015210012.0757.0312510017.7559.7526410022.6562.2892910033.3669.32658
10034.0969.6987610042.4373.0195410044.8373.7926810056.3674.33944 10079.474.73216
10090.9375.2012810102.7875.2480610113.9875.13283 10122.974.5278610137.4773.90916
#Mann= 3 , 0 , 0
9862.597    0.04       09862.597    0.04       010137.47    0.04       0
#XS Ineff= 2 , 0
       0                               0
Bank Sta=9862.597,10137.47
Exp/Cntr=0.3,0.1

Type RM Length L Ch R = 1 ,994.1191,138.243800,138.243800,138.243800
XS GIS Cut Line= 6
979494.465152631 752291.22502496979464.636939617752251.343355052
979451.795673739752217.998895198979458.679724166752129.560346113
979431.186781377752098.328964547979382.014311136 752066.19980123
#Sta/Elev= 30
9861.55881.408639869.72881.034289876.17280.523949886.243   79.559895.11778.90519
9907.08175.517039918.449 71.8265    994065.98483 9950.3162.09625 9960.3857.25909
9970.408 53.7882 9976.2352.099589980.55450.692219990.88448.4679810001.2745.72791
 10011.646.7573710021.8748.0095510028.6153.1649510032.0456.1063910037.7558.35687
10043.2461.2252210044.34 61.660710055.3964.9043410060.5465.9377310074.3466.82188
10087.1966.9678110111.6466.4709710123.2865.8584710134.9165.0327210138.3864.91705
#Mann= 3 , 0 , 0
9861.558   0.047       09861.558   0.047       010138.38   0.047       0
#XS Ineff= 2 , 0
       0                               0
Bank Sta=9861.558,10138.38
Exp/Cntr=0.3,0.1

Type RM Length L Ch R = 1 ,855.8753,138.243900,138.243900,138.243900
XS GIS Cut Line= 6
979636.114153761752088.305335416979595.188628264752078.423795699
979556.980705913 752073.90534233979449.450048909752080.996730165
979420.505043548752073.612502011979366.875256334752050.024498701
#Sta/Elev= 24
 9861.4966.610669875.57366.295349893.49866.014249903.78265.435929913.85164.99434
9923.92164.599359933.99164.415469944.047 65.00969954.05165.404499964.05466.34751
9974.07560.271199984.14351.782499994.21140.37006    999940.1307410004.2840.07373
10014.3545.8228410024.4250.3418510044.4563.0273210054.59 65.250310064.9165.63058
10085.8965.7317110096.8165.4982710118.6664.4166210138.4664.59492
#Mann= 3 , 0 , 0
 9861.49    0.04       0 9861.49    0.04       010138.46    0.04       0
#XS Ineff= 2 , 0
       0                               0
Bank Sta=9861.49,10138.46
Exp/Cntr=0.3,0.1

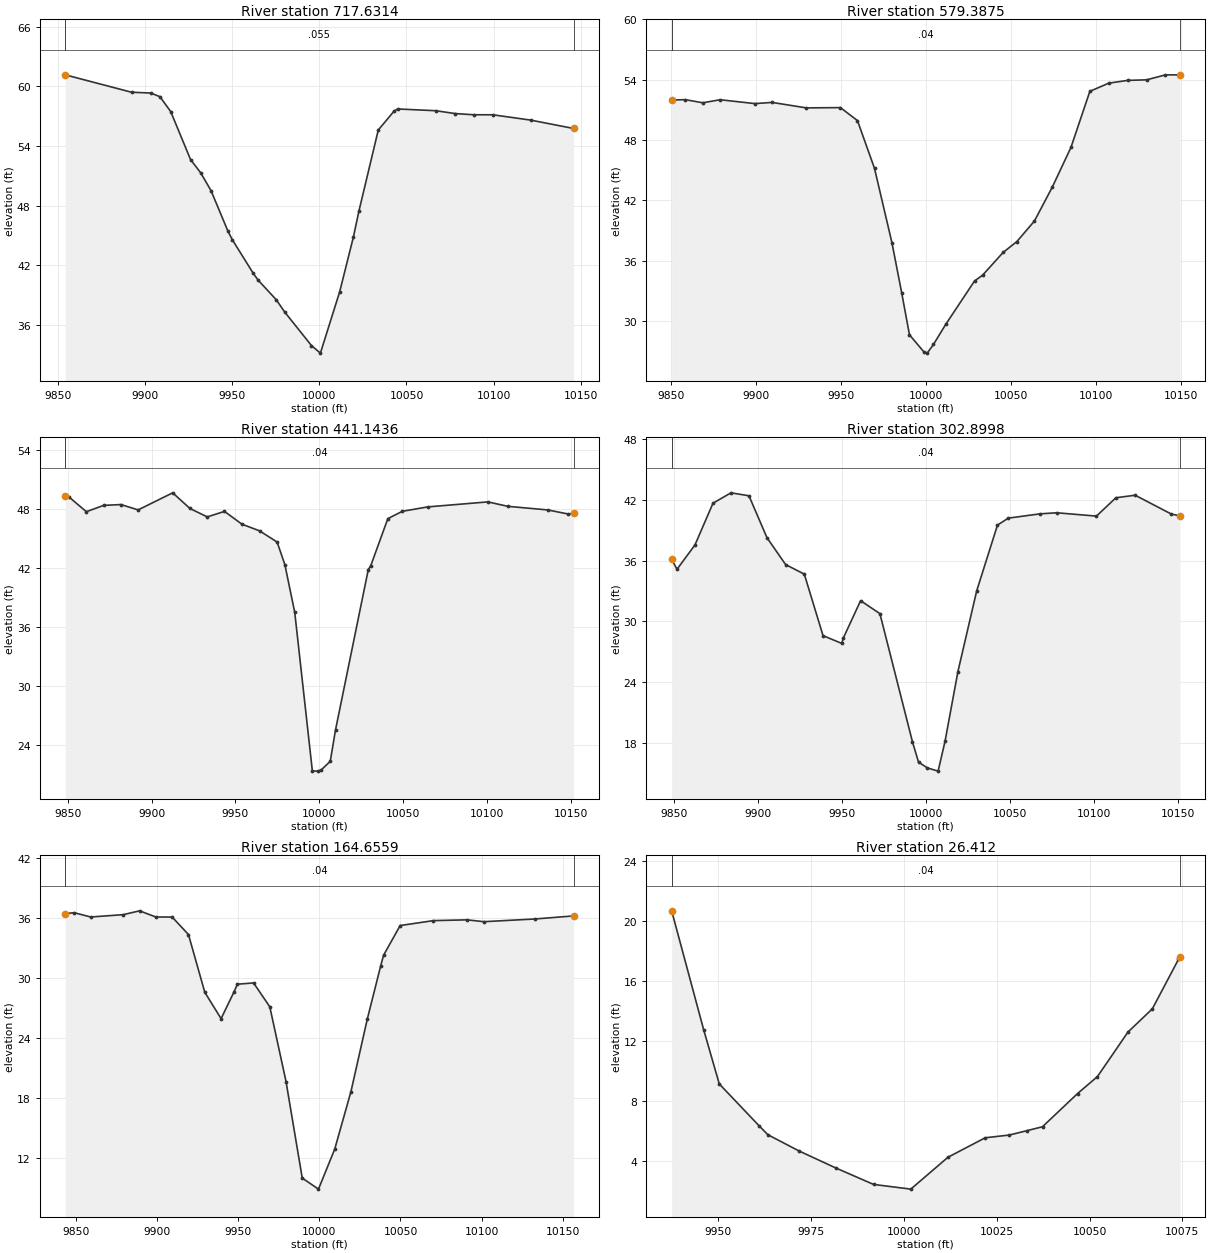
Type RM Length L Ch R = 1 ,717.6314,138.243900,138.243900,138.243900
XS GIS Cut Line= 6
979599.929168022752017.355442794979559.359858052751999.872081424
979529.865864572751983.822447146979504.948110232751966.662220498
979479.171750255751944.529625958979342.412215611751883.878205935
#Sta/Elev= 28
 9854.2161.147829892.24559.39876 9903.3559.31512 9908.5858.944969914.73557.45355
 9926.1252.631389931.96551.288019937.87349.498889947.51945.448569950.01544.58534
9962.15741.170499964.77140.526789975.33238.522539980.12237.297839995.47233.92813
10000.62 33.162210011.6739.3228910019.5344.8202810022.7547.4678510033.8355.59889
10042.7757.47326 10044.9 57.715410066.9257.5379610077.7957.2538710088.6757.13151
10099.5457.1295510121.2956.5939410145.8555.75342
#Mann= 3 , 0 , 0
 9854.21   0.055       0 9854.21   0.055       010145.85   0.055       0
#XS Ineff= 2 , 0
       0                               0
Bank Sta=9854.21,10145.85
Exp/Cntr=0.3,0.1

Type RM Length L Ch R = 1 ,579.3875,138.243900,138.243900,138.243900
XS GIS Cut Line= 6
 979722.92926901751889.250851259979621.238567698751873.931279819
979549.757497112 751894.83190556979532.941735082 751895.28432627
979501.590527352751886.609769778979437.277582039751855.357338273
#Sta/Elev= 30
9850.323 51.96399858.42151.996839868.63451.687459878.846 51.99089899.27251.60666
9909.45651.723469929.60251.17943 9949.6451.207859959.66549.919139969.70245.16242
9979.94937.783649985.71732.776489990.27828.61076    999926.8667110000.7126.78786
 10004.427.6488110011.63 29.649710028.5733.9615410033.3334.54184 10045.4  36.802
10053.4937.8840110063.8339.92643 10074.443.3173610085.3347.2492310096.4552.82594
10107.5753.6390410118.6853.91502 10129.853.9682210140.9254.4606910149.5154.46851
#Mann= 3 , 0 , 0
9850.323    0.04       09850.323    0.04       010149.51    0.04       0
#XS Ineff= 2 , 0
       0                               0
Bank Sta=9850.323,10149.51
Exp/Cntr=0.3,0.1

Type RM Length L Ch R = 1 ,441.1436,138.243800,138.243800,138.243800
XS GIS Cut Line= 6
979717.259553778751827.859556868979618.659158877751803.977852896
979571.966881038751789.037125209979563.325247232751785.633765373
979540.685589315751773.401488633979442.185773506751709.457210778
#Sta/Elev= 30
9848.52449.315439850.84949.200729861.13847.713879871.42748.356339881.71748.44025
9892.00647.898939912.58449.634279922.87348.040149933.16247.186039943.45147.74394
9953.81746.447689964.31745.768799974.81644.628339979.43442.323849985.31637.47416
9995.815 21.3419    999921.32565   1000121.4342610006.4822.3246610009.6225.52063
10029.1241.8055510030.6642.24124 10040.847.0094210049.4547.7550410064.6448.20358
10100.4148.7117910112.3348.2597410136.1847.89108 10148.147.4853710151.46 47.5336
#Mann= 3 , 0 , 0
9848.524    0.04       09848.524    0.04       010151.46    0.04       0
#XS Ineff= 2 , 0
       0                               0
Bank Sta=9848.524,10151.46
Exp/Cntr=0.3,0.1

Type RM Length L Ch R = 1 ,302.8998,138.243900,138.243900,138.243900
XS GIS Cut Line= 6
979777.954324611 751735.55513677979724.109580481751714.722864015
979677.310681902751691.604347105979639.358562977751669.914079702
979551.241236623751614.826722391979511.756993322751592.473955297
#Sta/Elev= 30
9848.54636.122259851.71335.137969862.43637.536749873.158 41.6412 9883.88 42.6648
9894.60342.375159905.32538.25453 9916.4435.604929927.59434.660089938.74828.60801
9949.90127.843829950.81128.363029961.13632.04871 9972.64 30.77389992.064 18.1446
9995.64916.16025   1000115.5846310007.3315.2722510011.4618.2110410019.1325.06959
10030.3333.0194610042.7139.4915110049.1940.1742910068.0640.5956710078.09 40.7008
10101.6840.3720210113.2842.1806710124.7742.4288910146.3640.5709610151.4840.39479
#Mann= 3 , 0 , 0
9848.546    0.04       09848.546    0.04       010151.48    0.04       0
#XS Ineff= 2 , 0
       0                               0
Bank Sta=9848.546,10151.48
Exp/Cntr=0.3,0.1

Type RM Length L Ch R = 1 ,164.6559,138.243900,138.243900,138.243900
XS GIS Cut Line= 6
979860.604720022751566.978488853 979757.13795164 751556.34610894
979687.824255589751555.234031079 979666.70861856751553.287272902
979625.605814878751544.132615942979552.041988114751522.169233233
#Sta/Elev= 28
9843.28236.458349848.916 36.54029858.96836.113459879.074 36.34529889.12636.73019
9899.17936.111799909.23236.107069919.28434.356679929.33728.58298 9939.3925.94212
9947.29328.593899949.43229.387849959.43529.514499969.43727.12399 9979.4419.64823
9989.4439.9857299999.4468.88113810009.4512.8793810019.4618.63603 10029.525.86603
10037.8331.2350810039.5832.2847510049.8235.2594110070.3135.7497510091.0135.82765
10101.4435.6436810132.75 35.913410156.71 36.2193
#Mann= 3 , 0 , 0
9843.282    0.04       09843.282    0.04       010156.71    0.04       0
#XS Ineff= 2 , 0
       0                               0
Bank Sta=9843.282,10156.71
Exp/Cntr=0.3,0.1

Type RM Length L Ch R = 1 ,  26.412,26.412000,26.412000,26.412000
XS GIS Cut Line= 4
 979750.78063044751434.500001758979733.412824422751415.304005623
979668.512075663751418.960385844979634.690558672751450.039617628
#Sta/Elev= 20
9937.52720.660089946.14312.723199950.3399.1138189961.0496.3232869963.4145.725842
 9971.844.6373089981.8563.4902229991.8722.40957410001.892.095826 10011.94.223881
10021.925.52083710028.425.70494410033.195.99719810037.346.25756710046.778.470406
10052.129.60087510060.3512.57529 10066.914.1197510073.9317.4178710074.3517.57971
#Mann= 3 , 0 , 0
9937.527    0.04       09937.527    0.04       010074.35    0.04       0
#XS Ineff= 2 , 0
       0                               0
Bank Sta=9937.527,10074.35
Exp/Cntr=0.3,0.1

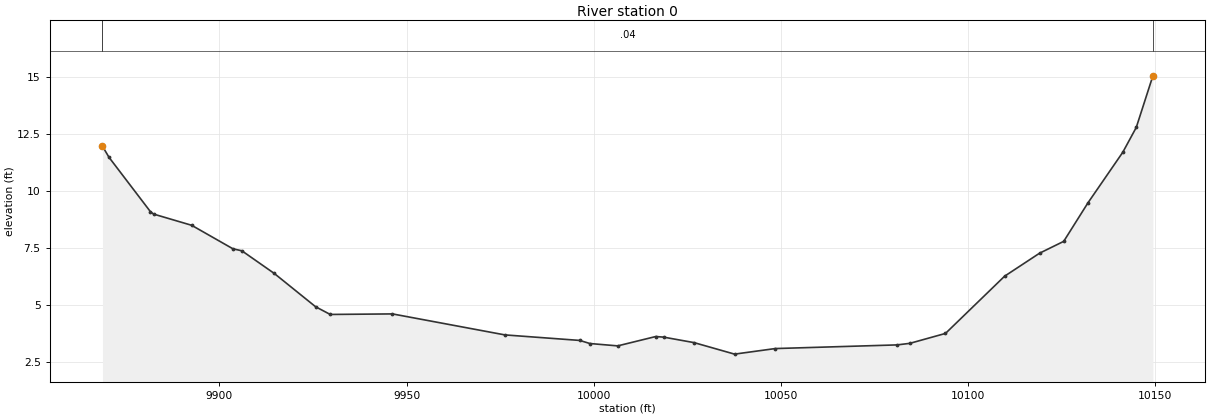
Type RM Length L Ch R = 1 ,       0,0.000000,0.000000,0.000000
XS GIS Cut Line= 6
979816.595474243751420.788575947 979759.92158094751394.279819399
979692.286033392751391.334205881979665.596241742751396.364638671
 979611.83818236751418.960385844979561.562954426751460.094663233
#Sta/Elev= 30
9868.73311.955049870.49511.465889881.5349.0907459882.3968.9804659892.5748.489475
9903.6147.4584719905.9987.3712619914.6546.3791789925.694 4.920549929.6014.583287
9946.2364.6067629976.2653.6872369996.2833.444787    99993.30923310006.423.206216
10016.593.61617310018.713.58902710026.813.34966710037.652.844948 10048.53.088607
10081.043.24887710084.47 3.3168310094.013.752062 10109.86.25838910119.157.266812
 10125.67.78569810132.07 9.4709710141.3911.6902810144.99 12.777310149.4315.03751
#Mann= 3 , 0 , 0
9868.733    0.04       09868.733    0.04       010149.43    0.04       0
#XS Ineff= 2 , 0
       0                               0
Bank Sta=9868.733,10149.43
Exp/Cntr=0.3,0.1